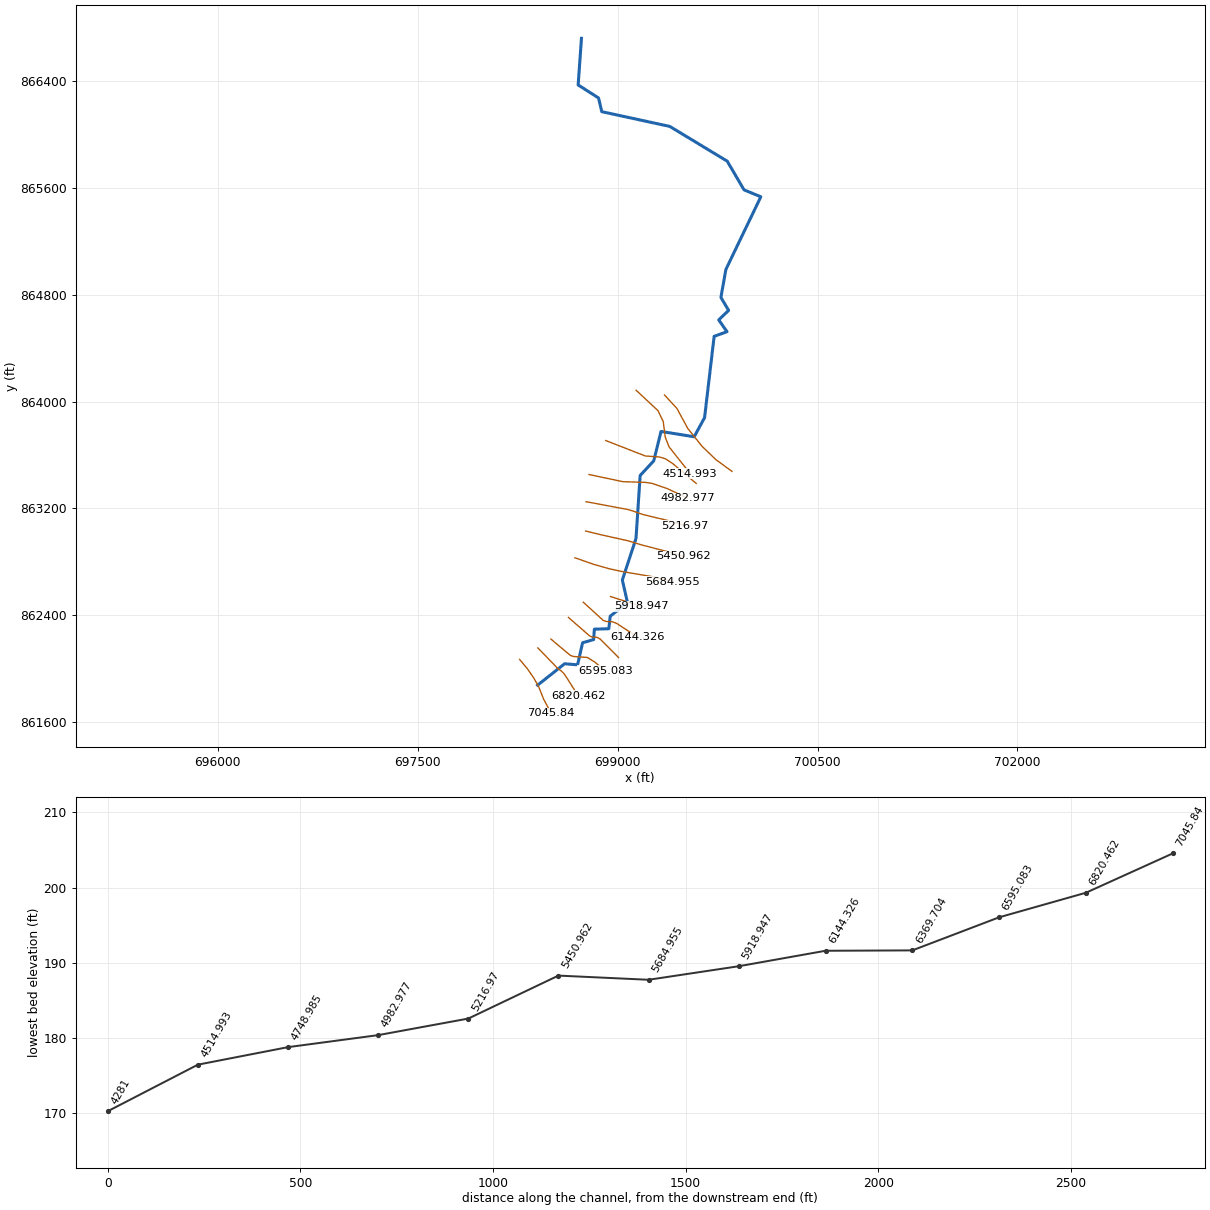
--- 13595_ras.prj (project) ---

Proj Title=13595
Current Plan=p01
Default Exp/Contr=0.3,0.1
English Units
Geom File=g01
Flow File=f01
Plan File=p01
Y Axis Title=Elevation
X Axis Title(PF)=Main Channel Distance
X Axis Title(XS)=Station
BEGIN DESCRIPTION:
RFD model 13595 exported to HEC-RAS
END DESCRIPTION:

--- 13595_ras.p01 (plan) ---

Plan Title=Plan 01
Program Version=4.10
Short Identifier=Plan 01
Geom File=g01
Flow File=f01
Subcritical Flow
Calc Critical at every XS
Secant Critical Depth

--- 13595_ras.f01 (steady flow) ---

Flow Title=Flow 01
Program Version=5.01
Number of Profiles= 6
Profile Names=10yr,25yr,50yr,100yr,100plus,500yr
River Rch & RM=13595,13, 7045.84
  534.87  877.93 1206.31 1513.65 2209.93 3340.07
River Rch & RM=13595,13,6820.462
  541.02  888.04 1220.22  1531.1 2235.41 3373.05
River Rch & RM=13595,13,6595.083
  560.48  920.05  1264.3 1586.44  2316.2 3477.45
River Rch & RM=13595,13,6369.704
  563.97  925.78 1272.18 1596.32 2330.63 3496.01
River Rch & RM=13595,13,6144.326
  569.23  934.41 1284.05 1611.19 2352.33 3523.79
River Rch & RM=13595,13,5918.947
  573.03  940.63 1292.59  1621.9 2367.97  3543.8
River Rch & RM=13595,13,5684.955
  942.74 1548.63 2130.05 2672.83 3902.34 5439.62
River Rch & RM=13595,13,5450.962
  945.88  1553.8 2137.17 2681.76 3915.38  5455.2
River Rch & RM=13595,13, 5216.97
  948.75 1558.53 2143.68 2689.94 3927.31 5469.47
River Rch & RM=13595,13,4982.977
   955.8 1570.12 2159.66 2709.99 3956.58 5504.43
River Rch & RM=13595,13,4748.985
  959.71 1576.55 2168.52 2721.11 3972.83 5523.82
River Rch & RM=13595,13,4514.993
  960.49 1577.83 2170.29 2723.34 3976.07 5527.69
River Rch & RM=13595,13,    4281
     967 1588.55 2185.06 2741.87 4003.12 5559.93
Boundary for River Rch & Prof#=13595,13,1
Up Type= 0
Dn Type= 2
Boundary for River Rch & Prof#=13595,13,2
Up Type= 0
Dn Type= 2
Boundary for River Rch & Prof#=13595,13,2
Up Type= 0
Dn Type= 2
Boundary for River Rch & Prof#=13595,13,2
Up Type= 0
Dn Type= 2
Boundary for River Rch & Prof#=13595,13,2
Up Type= 0
Dn Type= 2
Boundary for River Rch & Prof#=13595,13,2
Up Type= 0
Dn Type= 2

--- 13595_ras.g01 (geometry) ---

Geom Title=13595
Program Version=4.10

River Reach=13595,13
Reach XY= 30
698400.204791683861875.034200344698602.617782832862035.311773609
698699.924487241862027.378526207698737.638158954862192.784351808
698820.315032446862216.504746889698826.004107478862294.673359911
698933.989839816862297.811697263 698945.08059878862391.842044965
 699074.31205098862493.587703214699035.863020928862663.157195279
699138.230716731862974.440315597699169.441396798863446.619823245
699271.273250194863556.040594882699326.033340243863776.438561792
 699574.75789043863736.731954581 699652.72897205  863879.8689089
699724.325662134864489.299217339699820.843784839864524.174509717
699758.794837238864612.772691198699833.063569572864684.051128834
699775.129289864864781.207415479699812.749275501864991.092141179
700074.673570278865535.511479159699948.569540887865587.220877866
699822.834720758865802.173634529699391.964436555866062.685393663
698881.510607716866173.356260318698857.215254455866276.169234242
698704.312871786866373.558614642698729.182729466866722.980114953

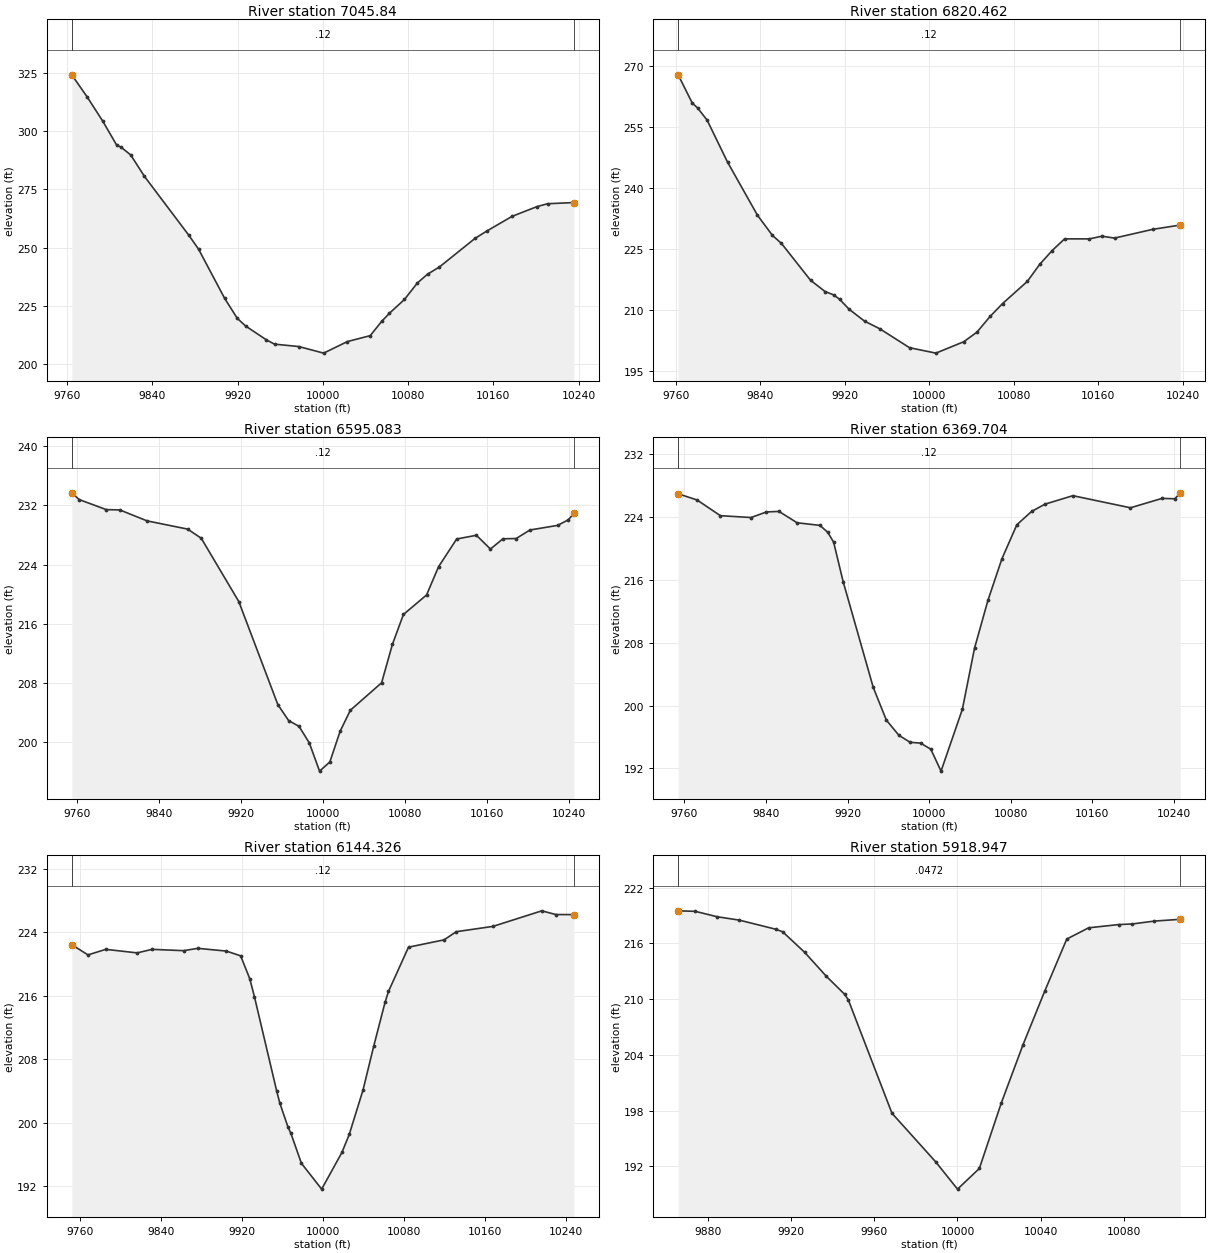
Type RM Length L Ch R = 1 , 7045.84,225.378600,225.378600,225.378600
XS GIS Cut Line= 6
698265.711693568862067.530843537698326.033235187861994.659071382
698371.479298136861928.187682702698407.063797396861865.664592211
698446.046300371861768.594237605698502.109742028861663.451872704
#Sta/Elev= 30
9764.517324.37799779.083314.76399793.765304.28789806.747294.01379810.448293.3069
9819.728  289.91 9832.71280.63099874.379255.24419883.409249.32819907.928228.0893
9919.769219.50429927.578216.20999947.077210.2425 9954.67208.39459977.408207.3682
10000.77204.529810023.06 209.51310044.45212.061910055.15218.176110062.25221.6136
10076.55227.642310088.77234.793910098.38238.5831 10109.3241.609910142.75253.9442
10153.96257.157410177.57263.451110200.55267.572610210.76268.863410235.48269.3743
#Mann= 3 , 0 , 0
9764.517    0.12       09764.517    0.12       010235.48    0.12       0
#XS Ineff= 2 , 0
       0                               0
Bank Sta=9764.517,10235.48
Exp/Cntr=0.3,0.1

Type RM Length L Ch R = 1 ,6820.462,225.378600,225.378600,225.378600
XS GIS Cut Line= 6
698402.061272806862154.434207647698545.533376069862006.109431769
698581.931917231 861977.51008946698595.302865784861964.115014381
698610.261822526 861943.71596944698706.236900982861793.156608237
#Sta/Elev= 30
9762.225267.89579775.528260.95339780.577259.73449789.628256.73849808.944246.3984
9837.312233.28869851.495228.32239860.046226.33929887.567 217.2679901.327214.4873
9909.593213.64989915.087212.57139924.151210.11439938.709207.18969953.267205.2906
9981.316200.6407 10006.3199.306310032.62202.107910045.18 204.47810057.58208.3399
10069.41211.519710092.91216.994210104.67 221.21110116.42224.598710128.17227.4669
10151.67 227.46110163.45228.121810175.46227.6577 10211.5229.808210237.74230.8753
#Mann= 3 , 0 , 0
9762.225    0.12       09762.225    0.12       010237.74    0.12       0
#XS Ineff= 2 , 0
       0                               0
Bank Sta=9762.225,10237.74
Exp/Cntr=0.3,0.1

Type RM Length L Ch R = 1 ,6595.083,225.378600,225.378600,225.378600
XS GIS Cut Line= 6
698499.571823374862220.659674823698645.107497099862098.676663087
698669.627864704862089.824800236698773.238998068862082.535952249
 698829.88721481862047.850358795698906.762359893861981.363325372
#Sta/Elev= 30
9755.204233.70189762.385232.79289788.843231.42989802.072231.3874 9828.53229.9093
9868.217228.79099881.445227.55629918.034218.9961 9956.17205.03269966.637202.8875
9976.776202.10049986.785199.87099996.795196.043510006.82197.280810016.84201.4328
10026.85204.2851 10057.3207.998610067.87213.212810078.57217.239910101.14  219.88
10112.86223.710110130.51227.456910149.74227.957510163.41226.0933 10175.6227.4813
10188.52227.518810201.91228.671810228.92229.296610239.39230.0562 10244.8230.9226
#Mann= 3 , 0 , 0
9755.204    0.12       09755.204    0.12       0 10244.8    0.12       0
#XS Ineff= 2 , 0
       0                               0
Bank Sta=9755.204,10244.8
Exp/Cntr=0.3,0.1

Type RM Length L Ch R = 1 ,6369.704,225.378600,225.378600,225.378600
XS GIS Cut Line= 6
698631.185058363 862382.53746506698790.958015434862243.712230734
698809.602310372862235.372724473698844.863067414862233.939381764
698868.776387283862220.902352172 699007.95908847862081.320332929
#Sta/Elev= 30
9753.878226.98359772.379226.19319795.281224.19129825.351223.95789840.386224.6667
9852.728224.73629870.455223.28969892.903222.95579900.525222.07179906.295220.8096
9915.577215.80079945.134202.30519957.953198.14989970.256196.21199981.295 195.321
9991.527195.218710001.54194.442110011.57191.648710032.49 199.53410044.38207.2995
10057.51 213.39110071.29218.714310085.89223.036110100.31224.728210113.36225.6565
10140.83226.741110197.29225.199210228.23226.397510240.79226.344610246.13227.1041
#Mann= 3 , 0 , 0
9753.878    0.12       09753.878    0.12       010246.13    0.12       0
#XS Ineff= 2 , 0
       0                               0
Bank Sta=9753.878,10246.13
Exp/Cntr=0.3,0.1

Type RM Length L Ch R = 1 ,6144.326,225.378600,225.378600,225.378600
XS GIS Cut Line= 6
698742.763901835862496.693630931   698892.310663862360.468732928
698914.438762682862352.163593638698962.226768311862349.733991751
698991.182197766862338.982526387699151.306816949 862235.00783647
#Sta/Elev= 30
9751.993222.45059768.014221.16729785.599 221.8659816.581221.41959831.285221.8658
9862.469221.69899876.552221.99339904.718221.64619918.801 221.0479927.889218.1304
9932.412215.8892 9954.49203.93479957.496202.46299965.565199.4289 9968.45 198.633
  9978.8194.86269998.818191.598310018.86196.2336 10026.1198.5116 10039.7204.1197
10050.39209.719710061.41215.163410064.84216.558710084.61222.139710119.75223.0645
10131.82224.0941   10168224.763610216.25226.728210230.11226.259610247.98226.2504
#Mann= 3 , 0 , 0
9751.993    0.12       09751.993    0.12       010247.98    0.12       0
#XS Ineff= 2 , 0
       0                               0
Bank Sta=9751.993,10247.98
Exp/Cntr=0.3,0.1

Type RM Length L Ch R = 1 ,5918.947,233.992500,233.992500,233.992500
XS GIS Cut Line= 2
698947.160799593862539.294619694699176.956814408862465.985461608
#Sta/Elev= 23
 9865.83219.49839874.058219.44389884.555218.85949895.051218.50439912.863217.5093
9916.044217.23829926.541215.04359937.037212.44559945.765210.52399947.534209.9268
9968.527197.7122 9989.52192.483510000.02189.543910010.51191.768910021.01198.7924
10031.51205.1027   10042210.9006 10052.5216.4607   10063217.671410077.38218.0179
10083.99218.084610094.49218.393210107.04 218.586
#Mann= 3 , 0 , 0
 9865.83  0.0472       0 9865.83  0.0472       010107.04  0.0472       0
#XS Ineff= 2 , 0
       0                10051.37       0
Bank Sta=9865.83,10107.04
Exp/Cntr=0.3,0.1

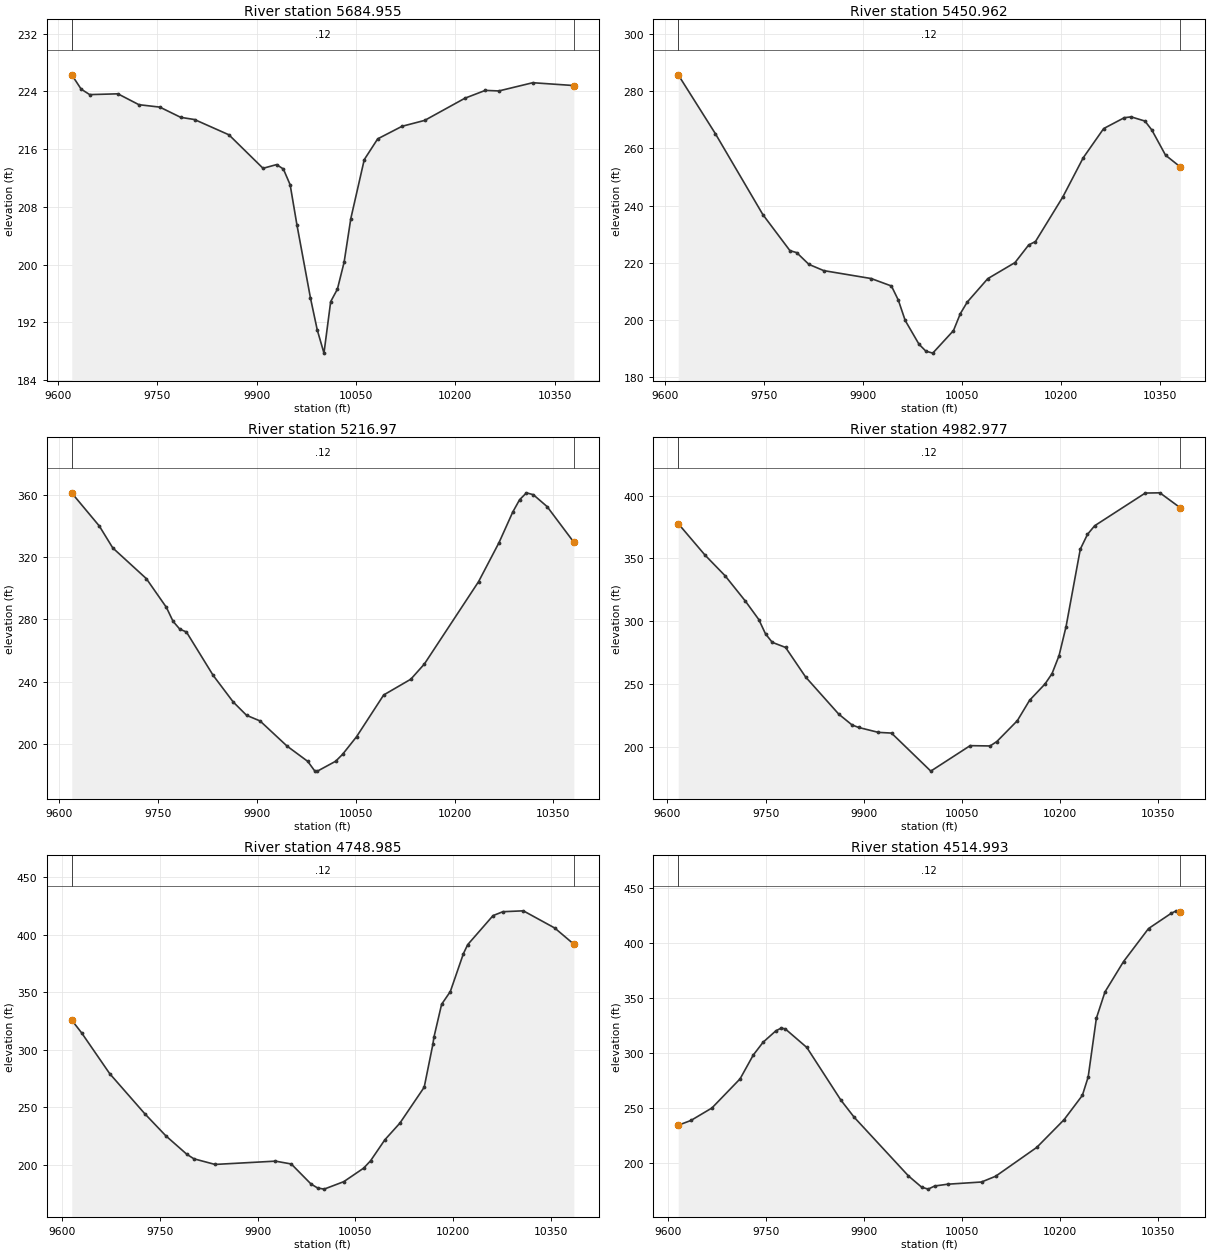
Type RM Length L Ch R = 1 ,5684.955,233.992400,233.992400,233.992400
XS GIS Cut Line= 6
698679.557143659862829.862173402698823.781268111862779.469774276
698939.508246099 862747.03638461699035.108418067862726.335890894
699266.669861664862687.186320867  699414.9808326862651.674508062
#Sta/Elev= 30
9620.904226.30539635.104224.32039647.983223.56449690.557223.67369722.265222.1678
9753.892221.83139785.405220.41439806.285220.11059858.212217.99519909.746213.3549
 9930.21213.86829940.441213.25539950.673211.07319960.905205.52629981.368195.3773
  9991.6 190.96510001.75187.745610011.89194.882410022.03196.609810032.17200.3425
10042.31206.3979 10062.6214.559110082.88217.434710119.65219.174610153.87219.9935
10214.72223.070510245.33224.147710265.81224.071710317.07225.212110379.09224.8194
#Mann= 3 , 0 , 0
9620.904    0.12       09620.904    0.12       010379.09    0.12       0
#XS Ineff= 2 , 0
       0                               0
Bank Sta=9620.904,10379.09
Exp/Cntr=0.3,0.1

Type RM Length L Ch R = 1 ,5450.962,233.992500,233.992500,233.992500
XS GIS Cut Line= 6
698760.356792384863030.132066339 698869.55547769863003.622449273
699077.299507501862957.258477453699187.347627321862924.186174954
699389.050879272862872.093665246699496.477269061862840.950186255
#Sta/Elev= 30
9619.849285.80389676.079265.19219748.044236.81949789.028224.20079799.274223.5053
9817.714219.39729840.258217.2034 9911.98214.43529942.718211.81949953.105 206.892
9963.534  199.759984.392191.4429 9994.82188.996110005.29188.300610036.64196.1952
10047.09202.162310057.53206.194910088.55214.387310129.86220.030210150.52226.1908
10160.84227.403110202.16242.987410233.14256.743510264.12266.982610295.33270.7818
10305.74271.073710326.56 269.61110336.97   266.5 10357.8257.652310380.16253.5379
#Mann= 3 , 0 , 0
9619.849    0.12       09619.849    0.12       010380.16    0.12       0
#XS Ineff= 2 , 0
       0                               0
Bank Sta=9619.849,10380.16
Exp/Cntr=0.3,0.1

Type RM Length L Ch R = 1 , 5216.97,233.992400,233.992400,233.992400
XS GIS Cut Line= 6
698763.974635717863249.992454185699073.437442288863192.143801877
699109.595740444863181.909392455699188.560367008863154.474891331
699382.441406778863107.636517932 699503.48089711863070.180618438
#Sta/Elev= 30
9618.878361.24719660.727340.02679681.128325.96689732.099306.23859762.531287.7843
9772.674278.81079782.818273.81529792.962271.97129833.537244.09699863.969227.0124
9884.263 218.4439904.693214.8382 9945.76198.65829977.062188.88049987.682182.7655
9991.838182.591910019.46 188.93610030.02193.391510051.16 204.66110092.41231.5188
10133.56241.629810154.13251.372710236.43304.285510267.47329.361810288.31348.9697
10298.74356.940310309.16361.360710319.58360.154710340.55 352.511 10381.1329.6195
#Mann= 3 , 0 , 0
9618.878    0.12       09618.878    0.12       0 10381.1    0.12       0
#XS Ineff= 2 , 0
       0                               0
Bank Sta=9618.878,10381.1
Exp/Cntr=0.3,0.1

Type RM Length L Ch R = 1 ,4982.977,233.992500,233.992500,233.992500
XS GIS Cut Line= 6
698785.272523592863453.935382807699039.361512842863400.067202369
699208.227458163863395.022722578699258.535283739863387.136600244
699372.614389488 863348.40063887699522.888710805863277.116892875
#Sta/Elev= 30
9616.539377.75449657.364 352.7119688.193336.14489719.022316.03019739.575301.2913
9749.852289.85849760.128283.1043 9780.53279.0119 9811.12255.45569861.834225.7845
9882.046217.20829892.087215.22089922.211211.29989942.293210.731110002.32180.3932
10062.44200.709510092.91200.463810103.25204.012110134.52220.634810153.24236.9075
10176.83249.918910187.53 258.19810198.23272.495910208.93295.682710230.67 357.385
10241.64369.184210252.61 376.058 10329.9402.137310352.26402.315110383.44390.3698
#Mann= 3 , 0 , 0
9616.539    0.12       09616.539    0.12       010383.44    0.12       0
#XS Ineff= 2 , 0
       0                               0
Bank Sta=9616.539,10383.44
Exp/Cntr=0.3,0.1

Type RM Length L Ch R = 1 ,4748.985,233.992400,233.992400,233.992400
XS GIS Cut Line= 6
698911.012354028863708.553334402699208.524810437863592.586781711
699314.407188732863585.186365235699358.607037717863571.765256083
699414.566029207863535.191126979699590.035811825 863386.72728075
#Sta/Elev= 30
9615.237 325.6679630.293 314.6969673.348279.21899727.166244.33549759.457225.1196
9791.747209.01769802.511205.14349834.802200.2663 9927.46203.12719951.631200.6597
9981.961183.21059991.967179.807910001.99178.797810032.06185.278510062.64197.0625
 10073.2203.474510095.11 221.72910118.08236.164110155.37267.3932 10168.7304.8114
10170.19310.653310182.04339.476110195.38 350.54410215.53383.642510222.05391.3563
10260.87 416.59510275.99419.987210307.31 420.74710355.41405.812410384.71391.7453
#Mann= 3 , 0 , 0
9615.237    0.12       09615.237    0.12       010384.71    0.12       0
#XS Ineff= 2 , 0
       0                               0
Bank Sta=9615.237,10384.71
Exp/Cntr=0.3,0.1

Type RM Length L Ch R = 1 ,4514.993,233.992500,233.992500,233.992500
XS GIS Cut Line= 6
699139.303734097864085.370456938699303.914922922863931.644643553
699342.739711298863850.098227521699357.759065942863733.666603817
699386.200706212863661.132101911699545.179375975863460.594506649
#Sta/Elev= 30
9615.111234.46299634.517238.77399666.762250.11489709.945 276.5679730.158298.1663
9745.305309.84119764.729320.0927    9773322.63869779.204321.8875 9812.29 305.026
9864.349257.37999884.757241.79719968.171188.41249988.304178.27039998.328176.4694
10008.34  179.3110028.38180.941610080.13 182.93410101.78188.150610164.83 214.334
10206.62239.417310234.77261.538910243.69278.278910256.26331.578410269.45355.4536
10297.89382.978310336.19412.9426 10370.6 426.62810378.72429.038310384.96428.2841
#Mann= 3 , 0 , 0
9615.111    0.12       09615.111    0.12       010384.96    0.12       0
#XS Ineff= 2 , 0
       0                               0
Bank Sta=9615.111,10384.96
Exp/Cntr=0.3,0.1

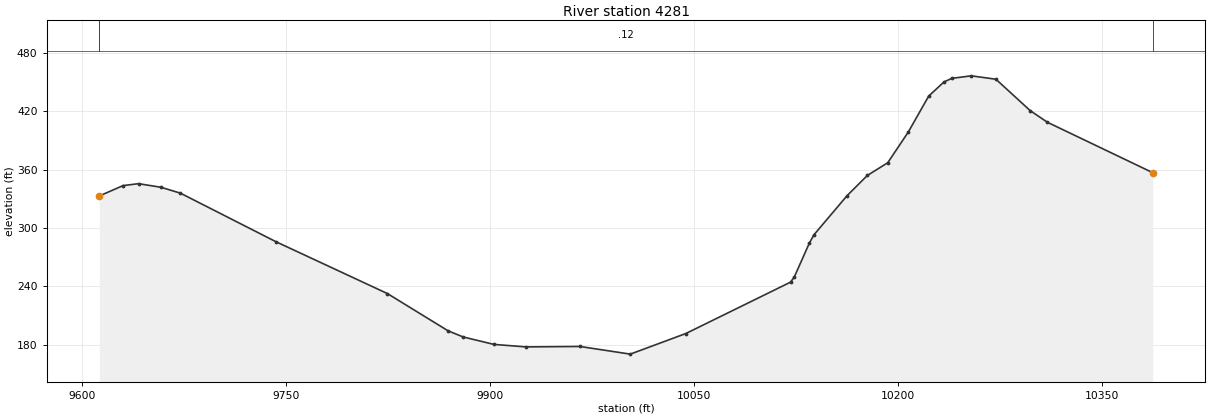
Type RM Length L Ch R = 1 ,    4281,0.000000,0.000000,0.000000
XS GIS Cut Line= 6
699352.085894655864049.932236194699445.273983067 863948.89167594
699526.343009691 863799.73705192699633.828485874863665.117885615
699739.267332736863563.739755717699858.715995878863476.869955796
#Sta/Elev= 30
9612.829332.86479630.231343.51019641.646345.49339658.109341.80589672.388335.7741
9742.718285.79569824.657232.49959869.195194.2543 9880.33187.91869902.849180.2894
9926.406177.70599966.067178.157410003.16170.284610043.96191.442710120.95244.2779
 10123.7249.5339 10134.8284.424710138.15292.921210162.49333.123910177.39353.9036
10192.44367.059210207.49398.497110222.53435.538410233.77450.068410239.48453.7437
10253.81456.360310271.94452.860510297.18420.542910309.79408.627610387.23356.7926
#Mann= 3 , 0 , 0
9612.829    0.12       09612.829    0.12       010387.23    0.12       0
#XS Ineff= 2 , 0
       0                               0
Bank Sta=9612.829,10387.23
Exp/Cntr=0.3,0.1